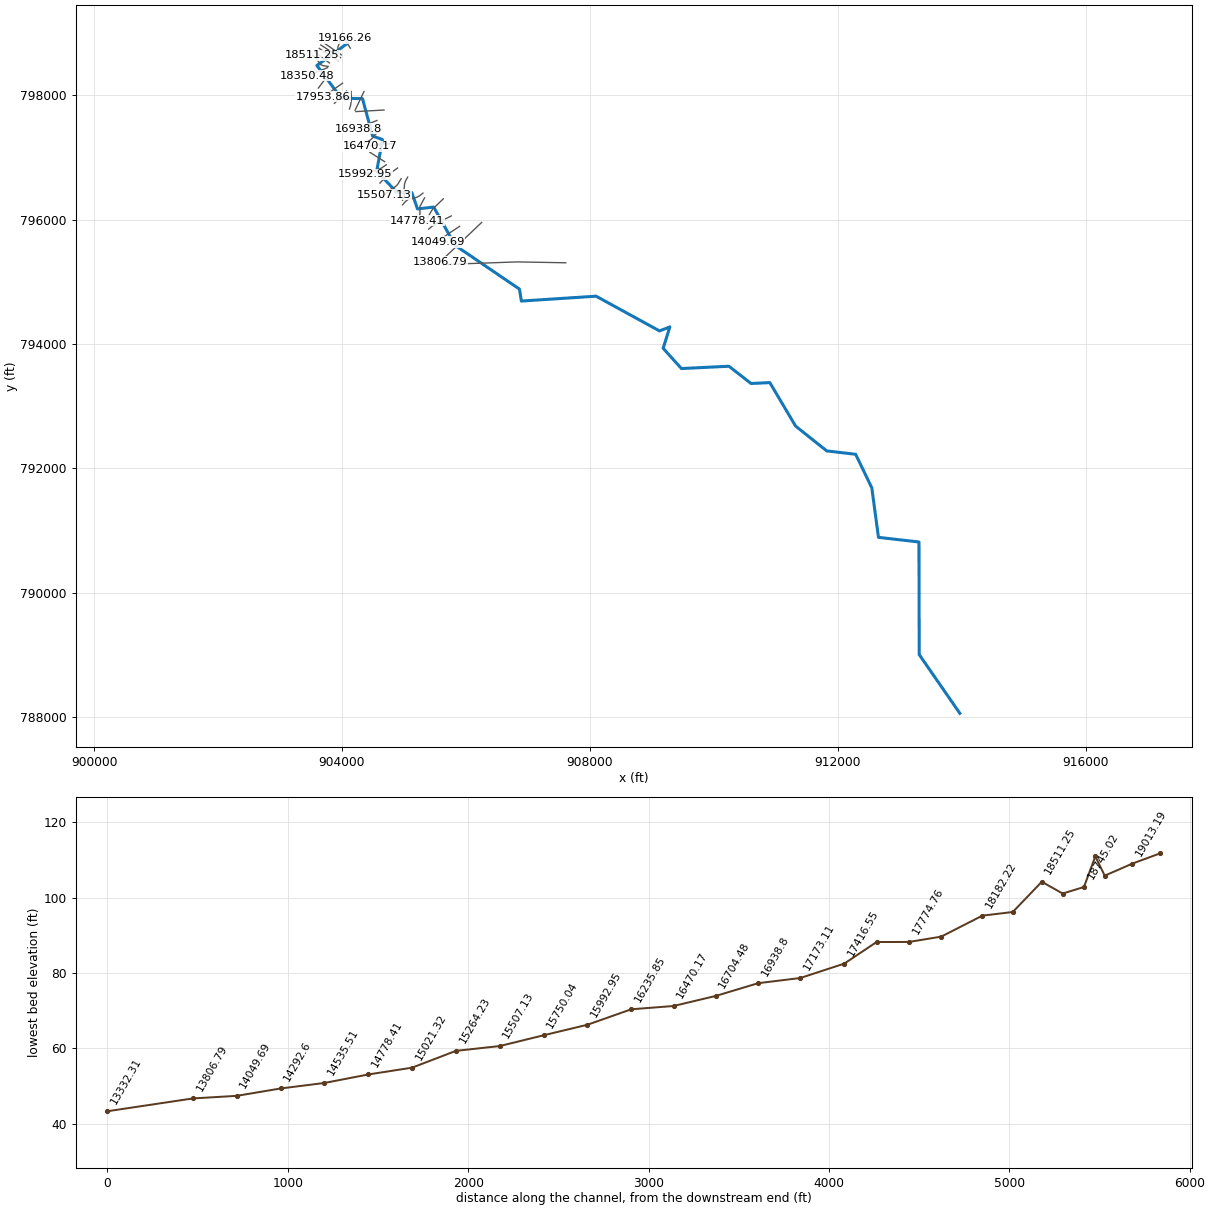
--- 12017_ras.prj (project) ---

Proj Title=12017
Current Plan=p01
Default Exp/Contr=0.3,0.1
English Units
Geom File=g01
Flow File=f01
Plan File=p01
Y Axis Title=Elevation
X Axis Title(PF)=Main Channel Distance
X Axis Title(XS)=Station
BEGIN DESCRIPTION:
RFD model 12017 exported to HEC-RAS
END DESCRIPTION:

--- 12017_ras.p01 (plan) ---

Plan Title=Plan 01
Program Version=4.10
Short Identifier=Plan 01
Geom File=g01
Flow File=f01
Subcritical Flow
Calc Critical at every XS
Secant Critical Depth

--- 12017_ras.f01 (steady flow) ---

Flow Title=Flow 01
Program Version=5.01
Number of Profiles= 6
Profile Names=10yr,25yr,50yr,100yr,100plus,500yr
River Rch & RM=12017,42,19166.26
   186.8  293.82  392.27  480.19  701.08 1180.49
River Rch & RM=12017,42,19013.19
  189.29   297.8  397.63   486.8  710.72 1194.66
River Rch & RM=12017,42,18807.98
  192.61  303.08  404.75  495.57  723.54 1213.45
River Rch & RM=12017,42,18627.15
  195.49  307.68  410.96  503.23  734.71  1229.8
River Rch & RM=12017,42,18511.25
  197.96  311.62  416.26  509.77  744.27 1243.75
River Rch & RM=12017,42,18350.48
  200.01  314.89  420.67  515.21  752.21 1255.33
River Rch & RM=12017,42,18182.22
  201.24  316.85  423.31  518.47  756.96 1262.25
River Rch & RM=12017,42,17953.86
  293.71  464.59  622.79  764.69 1116.44 1771.33
River Rch & RM=12017,42,17774.76
  312.52  494.76  663.64  815.21 1190.21 1873.15
River Rch & RM=12017,42,17595.65
  317.62  502.95  674.74  828.95 1210.27 1900.72
River Rch & RM=12017,42,17416.55
  321.33  508.87  682.73  838.81 1224.66 1920.31
River Rch & RM=12017,42,17173.11
  325.76  515.95  692.29  850.61 1241.89 1943.73
River Rch & RM=12017,42, 16938.8
  378.74  600.46  806.32  991.19 1447.13 2218.54
River Rch & RM=12017,42,16704.48
  410.42  651.49  875.61  1077.1 1572.56  2386.1
River Rch & RM=12017,42,16470.17
  416.62  661.45  889.11 1093.81 1596.97 2418.34
River Rch & RM=12017,42,16235.85
  424.11  673.51  905.49 1114.11  1626.6 2457.51
River Rch & RM=12017,42,15992.95
  433.93  689.32  926.96 1140.73 1665.47 2508.78
River Rch & RM=12017,42,15750.04
  439.36  698.05  938.81  1155.4 1686.88 2536.89
River Rch & RM=12017,42,15507.13
  446.47  709.49  954.32 1174.61 1714.93 2573.61
River Rch & RM=12017,42,15264.23
  457.96  727.96  979.36 1205.61 1760.19 2632.61
River Rch & RM=12017,42,15021.32
  460.94  732.76   985.9 1213.73 1772.04 2648.14
River Rch & RM=12017,42,14778.41
  466.95  742.44  999.03    1230  1795.8  2679.1
River Rch & RM=12017,42,14535.51
  483.31  768.75 1034.72  1274.2 1860.33 2762.68
River Rch & RM=12017,42, 14292.6
  505.71  804.96 1084.01 1335.43 1949.72 2878.71
River Rch & RM=12017,42,14049.69
  522.42  831.99 1120.82 1381.17  2016.5 2964.95
River Rch & RM=12017,42,13806.79
  537.41  856.23 1153.85 1422.22 2076.44 3042.06
River Rch & RM=12017,42,13332.31
  550.07  876.73 1181.79 1456.95 2127.15 3107.09
River Rch & RM=12017,42,12894.08
  949.18 1515.17 2045.38 2522.86 3683.37 4981.04
River Rch & RM=12017,42,11695.41
 1005.19 1606.29 2170.01 2678.18 3910.14 5249.92
River Rch & RM=12017,42,10816.98
  1045.7 1672.12    2260 2790.26 4073.77 5442.22
River Rch & RM=12017,42,10689.93
 1046.51 1673.44 2261.81 2792.52 4077.08 5446.11
River Rch & RM=12017,42,10226.64
 1062.04 1698.72  2296.4 2835.64 4140.03 5519.94
River Rch & RM=12017,42,10189.14
 1066.61 1706.18 2306.63 2848.41 4158.68 5541.89
River Rch & RM=12017,42,9948.777
 1094.98 1752.52 2370.17 2927.77 4274.55 5677.95
River Rch & RM=12017,42,7806.096
 1131.95 1813.02 2453.24 3031.64  4426.2 5855.73
River Rch & RM=12017,42,5047.063
 1827.84 2946.48 4005.43 4967.05  7251.9 9012.72
River Rch & RM=12017,42,2729.396
 1888.24 3047.23  4145.5 5144.03 7510.29 9300.76
River Rch & RM=12017,42,1375.701
 2771.16 4494.64 6136.81 7635.7411148.1813130.62
River Rch & RM=12017,42,      -0
 2883.19 4681.28 6396.25 7963.3311626.46 13630.6
Boundary for River Rch & Prof#=12017,42,1
Up Type= 0
Dn Type= 2
Boundary for River Rch & Prof#=12017,42,2
Up Type= 0
Dn Type= 2
Boundary for River Rch & Prof#=12017,42,2
Up Type= 0
Dn Type= 2
Boundary for River Rch & Prof#=12017,42,2
Up Type= 0
Dn Type= 2
Boundary for River Rch & Prof#=12017,42,2
Up Type= 0
Dn Type= 2
Boundary for River Rch & Prof#=12017,42,2
Up Type= 0
Dn Type= 2

--- 12017_ras.g01 (geometry) ---

Geom Title=12017
Program Version=4.10

River Reach=12017,42
Reach XY= 30
904088.772846643798832.870968881903595.532452147798476.544568706
903989.554096671797950.718191091904331.567985562797943.773746662
  904494.8326585797342.342487122904654.180952855 797286.36295721
904560.734652221796777.975135534904882.676494986796439.443662177
905126.619380951796435.329033177905218.828595436796170.935692343
905480.727815833796200.230740648905825.562057138795585.112507874
906863.911363337794881.278106319906894.664869639794689.311127272
908100.296396615 794767.31334435909123.910021515794208.987585509
909291.154019777794274.129259248909182.220138343793929.623916362
909477.734713766793604.098434203910243.437093912793641.104165421
910600.296396615 793363.66751103910903.681813274793377.990427682
911319.063619201792678.924027779911822.156400981792279.772107676
912288.665592435792225.060832728912548.852314236791686.276204379
 912656.28597999790889.709177696913309.931813266790815.490427691
 913313.83806327 789004.29251105913969.821708061788059.794933592

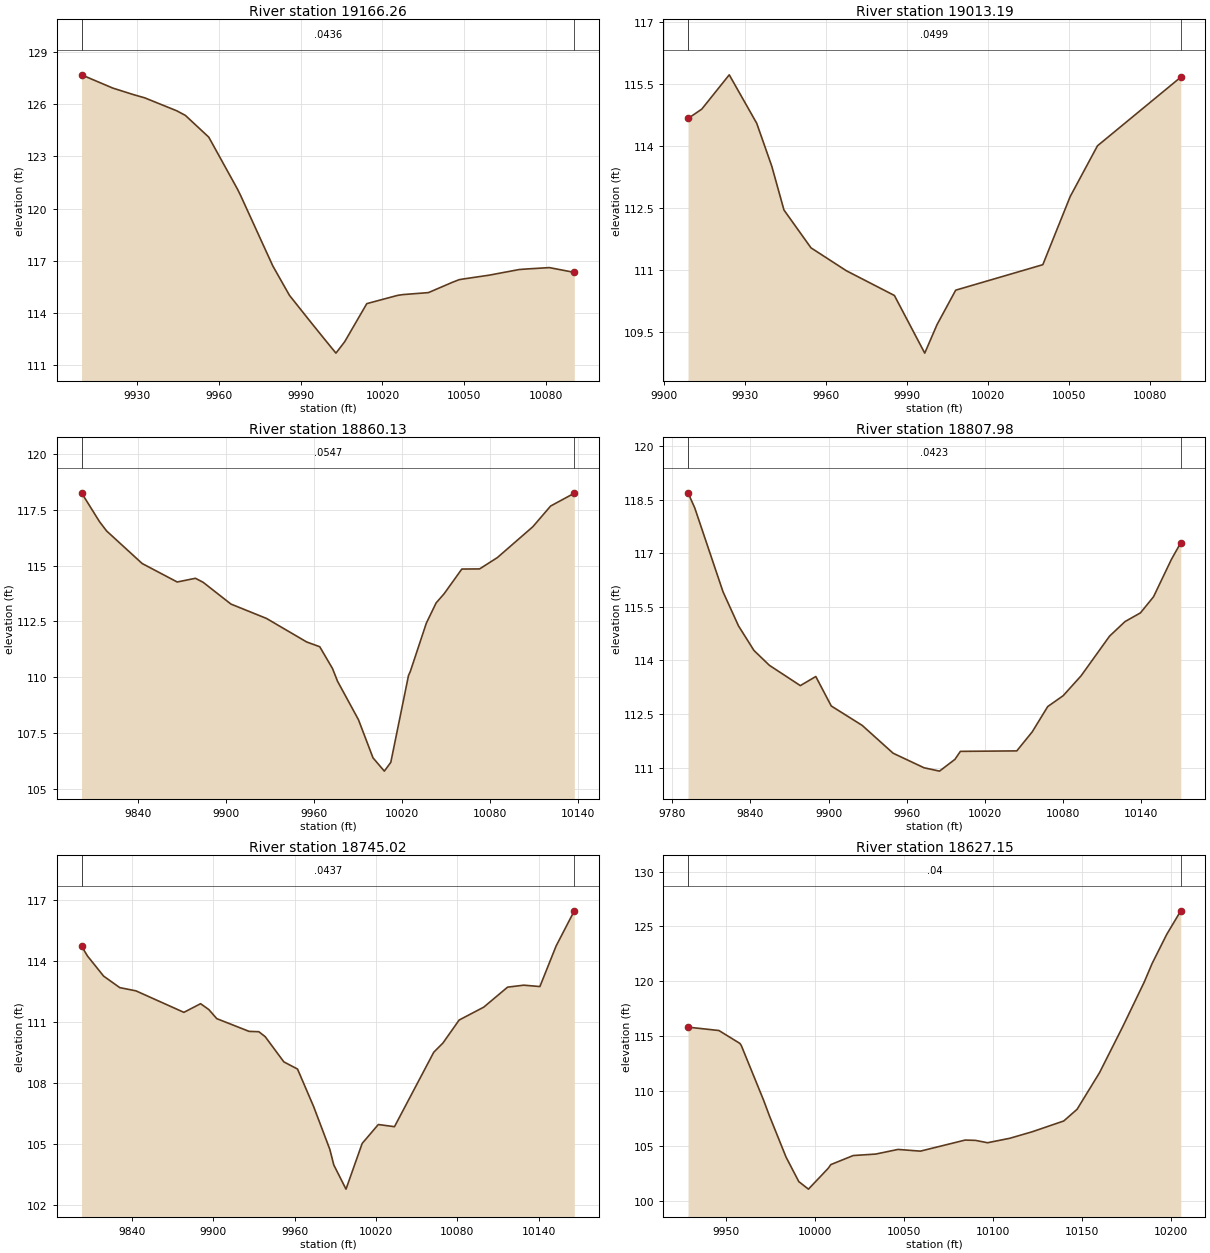
Type RM Length L Ch R = 1 ,19166.26,153.065900,153.065900,153.065900
XS GIS Cut Line= 6
904134.953759945798755.233746178  904090.7447612798827.145152324
904088.363587821798831.517267579 904087.41914534798833.280227703
904066.571430507798872.682461365904047.593548901798913.287199817
#Sta/Elev= 29
9909.608127.69569921.072126.93419928.614126.55979932.811126.37139944.549125.6267
9947.708125.36269956.288124.11239966.802121.12869968.026120.74019979.765116.7135
9985.896115.01679991.503113.91179994.022113.4161    9999112.4514   10001112.0672
10002.95111.695310006.17112.354710014.26114.540110025.57115.016110027.56115.0615
10036.89115.175110045.58115.760910048.14115.917910049.29115.949110059.17116.1777
10070.21 116.50210072.91116.533310081.25116.6122 10090.4116.3369
#Mann= 3 , 0 , 0
9909.608  0.0436       09909.608  0.0436       0 10090.4  0.0436       0
#XS Ineff= 2 , 0
       0                               0
Bank Sta=9909.608,10090.4
Exp/Cntr=0.3,0.1

Type RM Length L Ch R = 1 ,19013.19,153.065900,153.065900,153.065900
XS GIS Cut Line= 6
903939.861779669798719.993678571903934.030838187798750.503427288
903934.483849913798776.273994778903962.000869494798841.496082568
903965.872283848798866.301835002903964.773091996 798895.84914653
#Sta/Elev= 16
9908.725114.67059913.822114.89749924.003115.72829934.184114.55469939.787113.5101
9944.284112.45339954.286111.53819967.408110.98249985.199 110.3849996.442108.9873
   10001109.677810007.92110.5123 10040.2111.129510050.32112.777210060.44114.0083
10091.32115.6712
#Mann= 3 , 0 , 0
9908.725  0.0499       09908.725  0.0499       010091.32  0.0499       0
#XS Ineff= 2 , 0
       0                               0
Bank Sta=9908.725,10091.32
Exp/Cntr=0.3,0.1

Type RM Length L Ch R = 1 ,18860.13,52.146400,52.146400,52.146400
XS GIS Cut Line= 2
903989.115204539798648.061271928903711.667457014798838.376668991
#Sta/Elev= 28
9801.166118.25989813.433116.96659818.283116.55059842.536115.09269866.468 114.264
9878.916114.42949884.146114.25229903.169113.27429927.422112.6312 9954.86111.5765
9963.801111.36229972.539 110.3839975.928109.81849990.217108.095110000.18106.3821
 10007.9105.787810012.31106.180510024.43110.082110025.57110.242910036.56112.4161
10043.25113.325510048.69113.734910060.81 114.84410072.94114.849510085.07115.3576
10109.32116.741810121.45117.669210137.61118.2426
#Mann= 3 , 0 , 0
9801.166  0.0547       09801.166  0.0547       010137.61  0.0547       0
#XS Ineff= 2 , 0
       0                               0
Bank Sta=9801.166,10137.61
Exp/Cntr=0.3,0.1

Type RM Length L Ch R = 1 ,18807.98,62.961500,62.961500,62.961500
XS GIS Cut Line= 2
903977.650421584798602.202140106903658.929455418798806.275276716
#Sta/Elev= 26
9792.104118.68979797.292118.26669818.999115.91999830.873114.96739842.748114.2795
9854.622113.8631 9878.37113.29619890.245113.55069902.119112.72639925.867112.1835
9949.616111.40489973.364110.99779985.238110.90359997.112111.232810001.29111.4565
10044.61111.469610056.48112.002610068.36112.709610080.23113.013910094.01113.5708
10115.85114.679810127.73115.0875 10139.6115.331310149.65115.782610163.35116.8272
10170.56117.2924
#Mann= 3 , 0 , 0
9792.104  0.0423       09792.104  0.0423       010170.56  0.0423       0
#XS Ineff= 2 , 0
       0                               0
Bank Sta=9792.104,10170.56
Exp/Cntr=0.3,0.1

Type RM Length L Ch R = 1 ,18745.02,117.873700,117.873700,117.873700
XS GIS Cut Line= 2
903938.670159535798554.050051692903633.706932915798751.244318529
#Sta/Elev= 30
9802.971114.72949807.342114.2457 9819.25113.25659831.159112.69089843.067112.5326
9878.387 111.4769890.701 111.9019896.804111.61069902.609111.16739926.426110.5408
9933.637110.52349938.335 110.2799952.053109.04229962.152 108.687 9974.06106.8366
9985.969104.73639988.886103.97129997.877102.784110009.79105.030310021.69105.9606
 10033.6105.854310062.55109.514110069.33109.968310081.24111.096910099.39111.7311
10116.96112.714810128.87112.811610140.78112.744210152.69114.733210166.14116.4671
#Mann= 3 , 0 , 0
9802.971  0.0437       09802.971  0.0437       010166.14  0.0437       0
#XS Ineff= 2 , 0
       0                               0
Bank Sta=9802.971,10166.14
Exp/Cntr=0.3,0.1

Type RM Length L Ch R = 1 ,18627.15,115.894700,115.894700,115.894700
XS GIS Cut Line= 2
903798.799807476798517.362746234903578.675974729798684.748577386
#Sta/Elev= 28
9928.732 115.8219946.068115.5136 9957.87114.33429958.631114.14849971.194109.1408
9974.391107.74659983.757103.97139990.912101.73569996.319101.052410007.43102.9547
10008.88103.289310021.45104.115210034.01104.246810046.57104.671910059.13104.5158
10084.26105.525210090.04105.497910096.82105.281910109.38105.690210121.95106.2852
 10139.6107.266110147.07108.329310159.64111.661110172.64115.845210184.76119.9297
10189.16121.615110197.32124.258410205.27126.4254
#Mann= 3 , 0 , 0
9928.732    0.04       09928.732    0.04       010205.27    0.04       0
#XS Ineff= 2 , 0
       0                               0
Bank Sta=9928.732,10205.27
Exp/Cntr=0.3,0.1

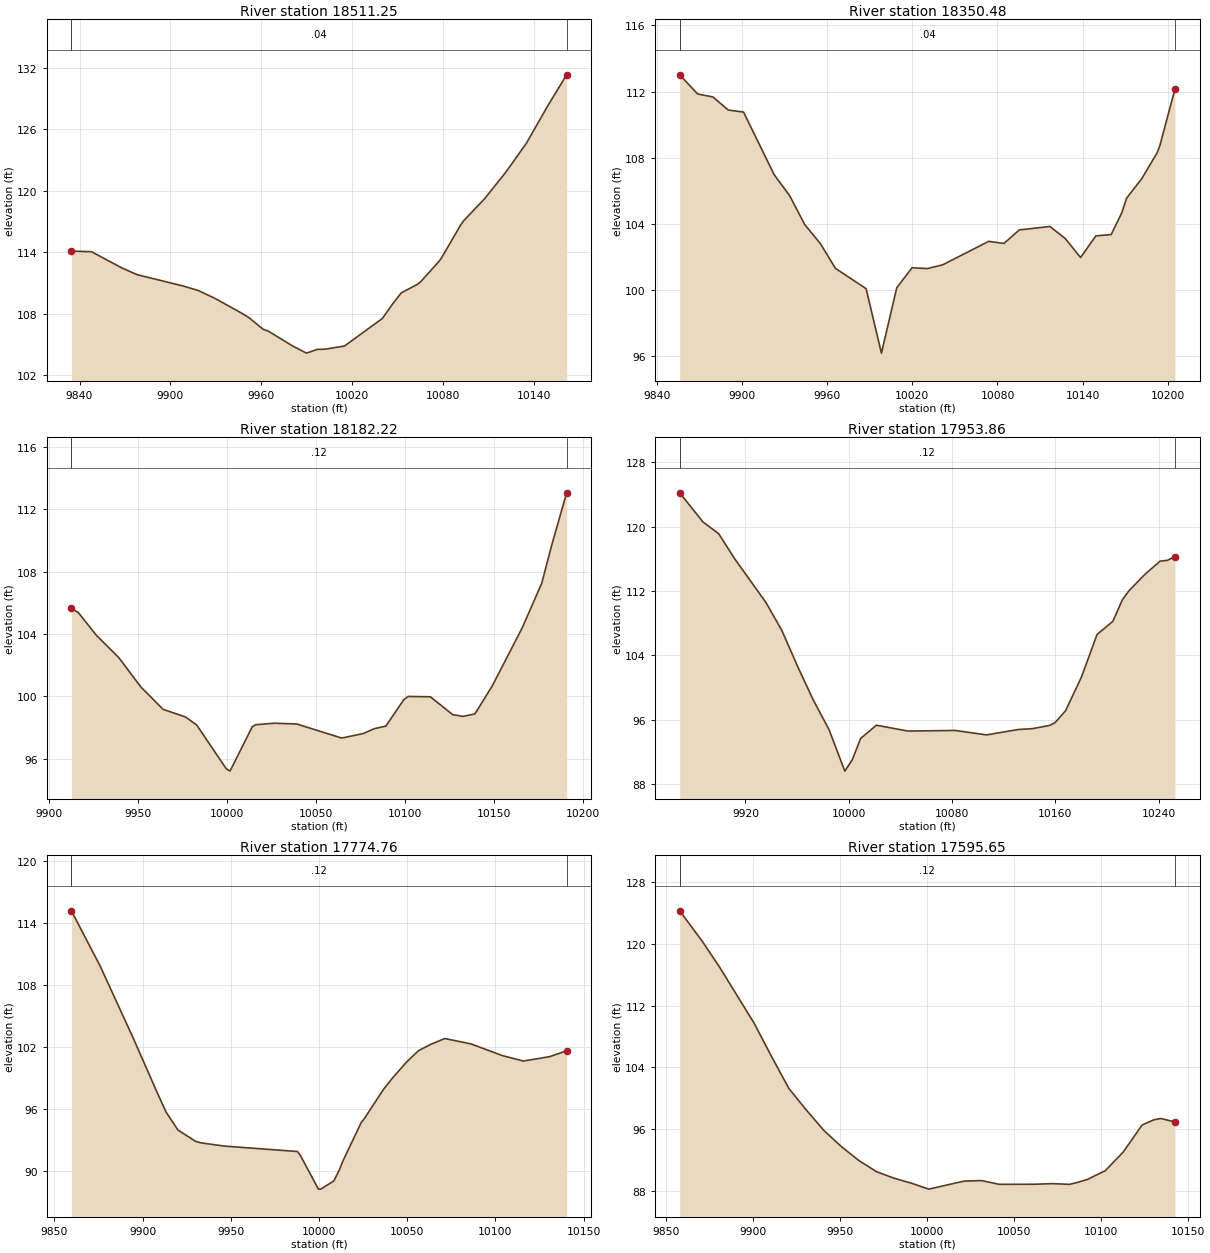
Type RM Length L Ch R = 1 ,18511.25,160.768800,160.768800,160.768800
XS GIS Cut Line= 5
903778.163198156798462.331788047903693.323804285798473.796571003
903656.636498827798492.140223732903585.554844502798586.151443968
903525.937973133798643.475358746
#Sta/Elev= 30
9834.647114.1212 9847.93 114.0629868.112112.47029878.202111.81779908.475110.7198
9918.566 110.2759929.564109.50139945.309108.21899951.924107.63159961.275106.4964
 9964.86106.30679980.569104.88449989.934104.1696 9997.15104.535210002.47104.5582
10015.01104.860510040.08107.548410046.89 108.97210052.62110.055110063.47   110.9
10065.15111.097110077.69113.153910079.13113.4537 10091.9116.691810093.78117.0823
10107.65119.235810121.52121.797210135.18124.634310149.61  128.3610161.84131.3208
#Mann= 3 , 0 , 0
9834.647    0.04       09834.647    0.04       010161.84    0.04       0
#XS Ineff= 2 , 0
       0                               0
Bank Sta=9834.647,10161.84
Exp/Cntr=0.3,0.1

Type RM Length L Ch R = 1 ,18350.48,168.260300,168.260300,168.260300
XS GIS Cut Line= 2
903766.698415201798441.695178727903443.391535852798310.996653033
#Sta/Elev= 30
9856.222113.0099 9868.84111.85099879.627111.66859890.413 110.8779901.199 110.754
9922.771106.95769933.558105.70079944.344103.9306 9955.13102.80679965.916101.2863
9987.489100.05589998.27596.1533910009.06100.109210019.85101.324510030.63101.2749
10041.42 101.50210073.78102.923110084.56102.796910095.35103.615810116.92103.8251
10127.71103.0956 10138.5101.945510149.28103.255510160.07103.335910167.58104.6647
10170.85105.528310181.64106.727910192.43108.289410194.27108.701810204.95112.1403
#Mann= 3 , 0 , 0
9856.222    0.04       09856.222    0.04       010204.95    0.04       0
#XS Ineff= 2 , 0
       0                               0
Bank Sta=9856.222,10204.95
Exp/Cntr=0.3,0.1

Type RM Length L Ch R = 1 ,18182.22,228.360800,228.360800,228.360800
XS GIS Cut Line= 2
903787.335024521798336.219175535903619.949193369798113.802386197
#Sta/Elev= 30
9912.357105.6383 9916.24105.37719926.398103.91369938.913102.49329951.429100.5897
9963.94499.15328 9976.4698.67103 9982.7698.155579999.39195.3395210001.49 95.1887
10014.0198.0423910016.0298.1715910026.52 98.267210039.0498.2171910064.0797.31959
10065.9197.3502510076.5897.6107310082.5497.91392 10089.198.0820610099.1799.77766
10101.61  99.98910114.1399.9641710126.6598.8191510132.4398.7069610139.1698.86375
10149.06100.698110165.69104.382910176.71107.255310182.32109.714110190.72113.0706
#Mann= 3 , 0 , 0
9912.357    0.12       09912.357    0.12       010190.72    0.12       0
#XS Ineff= 2 , 0
       0                               0
Bank Sta=9912.357,10190.72
Exp/Cntr=0.3,0.1

Type RM Length L Ch R = 1 ,17953.86,179.103400,179.103400,179.103400
XS GIS Cut Line= 2
 904009.75181386798191.762910295903695.616760876797971.639077547
#Sta/Elev= 30
9869.059 124.2169887.072120.59759899.283119.12739911.493116.05369935.915110.5702
9948.126 107.1289960.336 102.6579972.54798.456149984.75894.767729996.96989.62037
10002.8291.0610710009.1893.6776310021.3995.3270610045.8194.6028810082.4494.67568
10106.8794.1253710131.2994.7952810142.2394.8984310155.7195.3096110159.6695.62559
10167.9297.1226710180.13101.270210192.34106.613410204.55108.237310211.93110.9152
10216.76111.984510229.36114.079610241.18115.727810246.78115.822710252.64 116.293
#Mann= 3 , 0 , 0
9869.059    0.12       09869.059    0.12       010252.64    0.12       0
#XS Ineff= 2 , 0
       0                               0
Bank Sta=9869.059,10252.64
Exp/Cntr=0.3,0.1

Type RM Length L Ch R = 1 ,17774.76,179.103300,179.103300,179.103300
XS GIS Cut Line= 6
904073.743019617798066.023784706904041.384199325 798014.96059539
904014.320769698797982.723643488903996.429563129797966.862525587
903952.739255223797936.506694359903878.037322157  797868.4395838
#Sta/Elev= 29
9859.645115.19519875.978109.82319894.661102.85889908.21297.590729913.34395.66896
9920.05193.935829930.02792.840649933.10392.69305 9946.1692.382239987.79791.85255
9989.54491.448119999.65988.21576   1000188.2050710008.42 88.997510011.3990.01332
10013.8291.0234210023.8694.63466 10025.594.9848810036.5197.8645310041.6198.96617
10049.84100.563510056.45101.637410063.37102.2382 10071.3102.811110086.15102.2915
10103.95101.157810115.84100.626610130.69101.049410140.43101.6168
#Mann= 3 , 0 , 0
9859.645    0.12       09859.645    0.12       010140.43    0.12       0
#XS Ineff= 2 , 0
       0                               0
Bank Sta=9859.645,10140.43
Exp/Cntr=0.3,0.1

Type RM Length L Ch R = 1 ,17595.65,179.103400,179.103400,179.103400
XS GIS Cut Line= 6
904149.358021828798057.763103126904148.167191679798021.492841621
904153.947180901797953.482740534904153.555354825797929.583386906
904138.262371449797830.712435936904120.567610485797777.413735255
#Sta/Elev= 28
9857.642124.31329870.412120.42729880.417117.06369900.448109.72519910.484105.3881
 9920.52101.22259930.55698.431099940.592  95.7989950.62893.705729960.66491.90455
9970.67190.472069980.672 89.62519990.71888.9728410000.8288.1916610021.07  89.229
10031.1989.3032610041.3188.8160710061.5588.8212410071.6888.90601 10081.888.81157
10086.1489.0527210092.0689.4490410102.4390.5994310112.7993.0438910123.4896.50876
10130.2797.1862910134.2397.3608810142.3896.91117
#Mann= 3 , 0 , 0
9857.642    0.12       09857.642    0.12       010142.38    0.12       0
#XS Ineff= 2 , 0
       0                               0
Bank Sta=9857.642,10142.38
Exp/Cntr=0.3,0.1

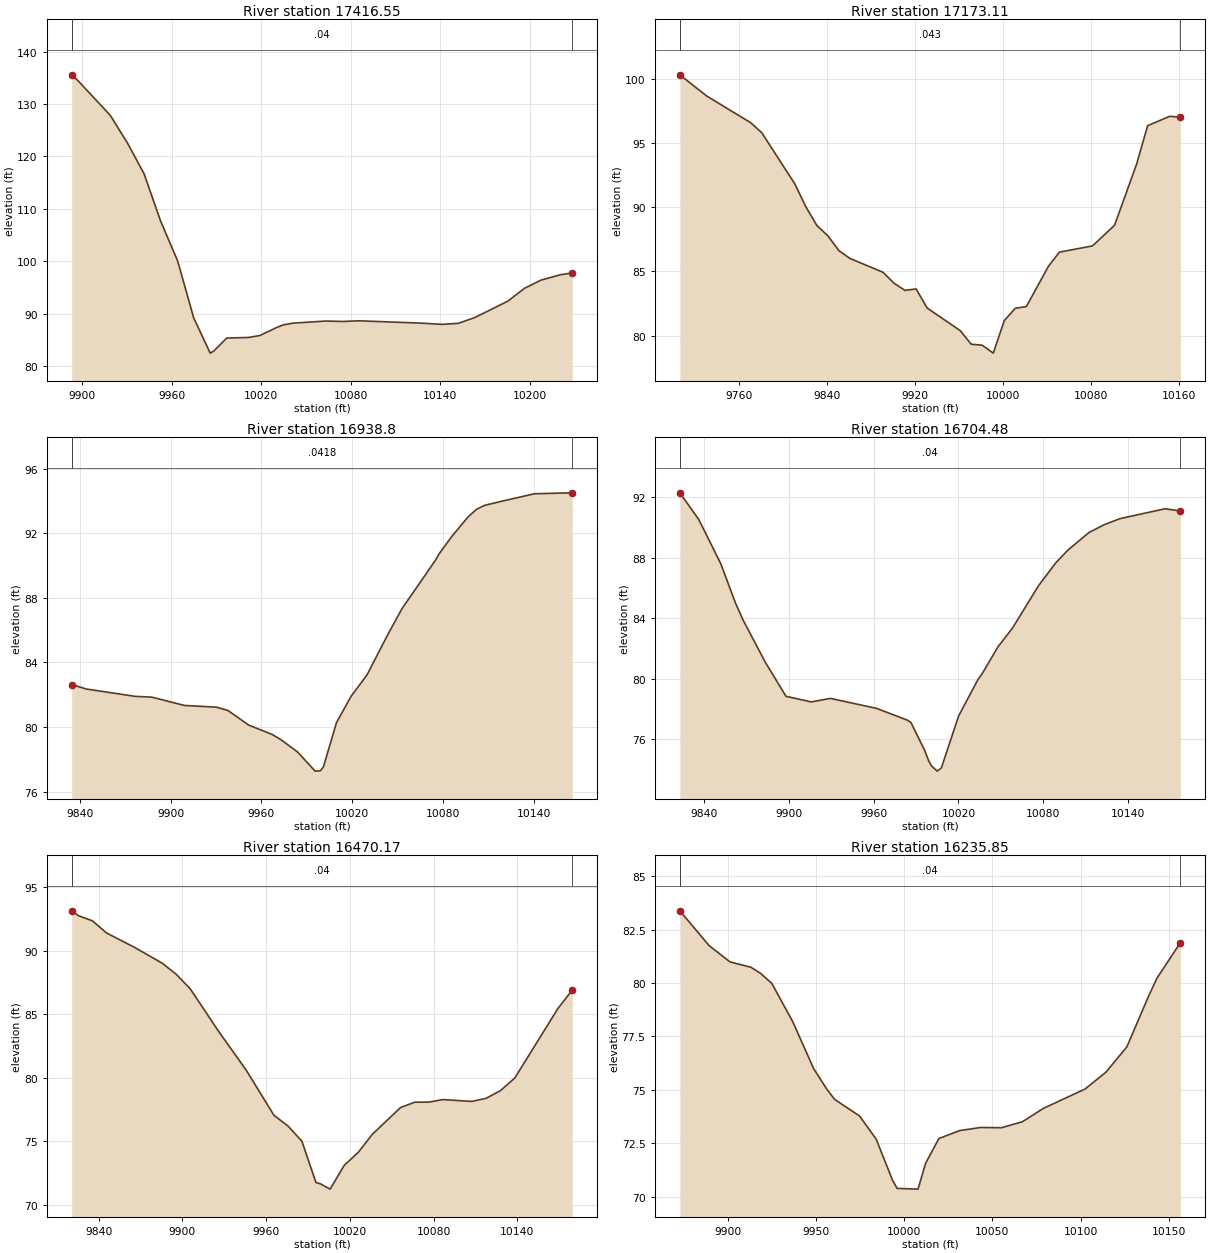
Type RM Length L Ch R = 1 ,17416.55,243.439400,243.439400,243.439400
XS GIS Cut Line= 2
904355.988259119 798058.77142801904211.531993878797756.101157981
#Sta/Elev= 30
9892.923135.56549897.102 134.4679918.434127.94069919.263127.62319930.343122.5215
9941.424116.68049952.504107.66399963.585100.26829964.86699.105659974.66689.19344
9985.74682.461549988.083 82.85119996.82785.33688 10011.385.4474410018.9985.81972
10030.0787.3189410034.5287.8375610041.1588.1838410063.3188.5872810074.3988.50312
10085.4788.6281710127.3888.1800910140.8787.9526310151.9588.1431910163.0489.25277
 10185.2 92.386610196.2894.8247110207.3696.3905810220.2597.40932 10228.397.76276
#Mann= 3 , 0 , 0
9892.923    0.04       09892.923    0.04       0 10228.3    0.04       0
#XS Ineff= 2 , 0
       0                               0
Bank Sta=9892.923,10228.3
Exp/Cntr=0.3,0.1

Type RM Length L Ch R = 1 ,17173.11,234.314100,234.314100,234.314100
XS GIS Cut Line= 2
904679.295138467797760.687071164904225.289733425797735.464548661
#Sta/Elev= 30
9706.619100.29429730.95198.652349771.01396.568299781.02995.793479811.07591.81076
 9821.0990.032469831.10688.572659841.12187.773929851.13686.620229861.15286.01453
9891.19884.938519901.21484.082859911.22983.528839921.24483.64259 9931.2682.15891
9961.30680.401389971.32279.342099981.33779.264239991.35278.6498810001.3781.18636
10011.3882.13827 10021.482.2720610041.4385.3995310051.4486.5045110081.4986.98862
10101.5288.5934910121.5593.3507410131.5796.33883 10151.697.0667310161.3297.00718
#Mann= 3 , 0 , 0
9706.619   0.043       09706.619   0.043       010161.32   0.043       0
#XS Ineff= 2 , 0
       0                               0
Bank Sta=9706.619,10161.32
Exp/Cntr=0.3,0.1

Type RM Length L Ch R = 1 , 16938.8,234.314100,234.314100,234.314100
XS GIS Cut Line= 6
904564.011304663797592.703539517904498.189822285797566.087949324
904428.305688674797540.499372513904396.656453316797520.725516133
904373.379407313797508.480002367904262.144284128797459.563893186
#Sta/Elev= 28
9834.71782.628749844.43782.351539876.797 81.89529887.58381.850589909.11381.33454
9930.41181.227289937.96481.01933 9951.7180.113149967.04879.541019973.00879.20798
9983.95778.446419995.51177.26463    999977.28458   1000177.5376410009.6680.28178
10019.3781.9167810029.7983.22997 10043.885.7790210052.9587.34286 10074.890.30747
10077.2990.7146310085.7391.8017610096.6593.0317510102.1393.4885210107.5793.73469
 10118.593.9824210140.3594.4515910165.3194.50861
#Mann= 3 , 0 , 0
9834.717  0.0418       09834.717  0.0418       010165.31  0.0418       0
#XS Ineff= 2 , 0
       0                               0
Bank Sta=9834.717,10165.31
Exp/Cntr=0.3,0.1

Type RM Length L Ch R = 1 ,16704.48,234.314100,234.314100,234.314100
XS GIS Cut Line= 6
904635.373065997797453.486927855904531.077594484797361.147349835
904494.484532224797312.412064736904469.718790939797287.580581088
904424.661449571797257.093738119 904366.19436773797230.464686696
#Sta/Elev= 30
9822.83192.277929836.296 90.50569851.82687.589359862.25884.984089867.51183.89081
9883.19581.106459897.92578.838079915.78778.464229929.46678.697699962.19178.03417
9983.82377.260669986.41377.104859995.93375.29531    999974.56448   1000174.23293
   1000573.8922510007.9174.1053210020.1377.5364310033.7679.9314410036.72 80.3183
10047.8882.0910310058.3683.3552410076.8186.1594610089.0587.6709310097.5988.50398
10112.4489.6584510123.4590.1844310134.4490.5751210166.1491.2227910177.0891.08444
#Mann= 3 , 0 , 0
9822.831    0.04       09822.831    0.04       010177.08    0.04       0
#XS Ineff= 2 , 0
       0                               0
Bank Sta=9822.831,10177.08
Exp/Cntr=0.3,0.1

Type RM Length L Ch R = 1 ,16470.17,234.314100,234.314100,234.314100
XS GIS Cut Line= 6
904809.830396487797220.691085599904739.137746377797215.497876882
904658.936498554 797218.51063782904640.466162889797217.857160301
904551.697351751797204.600286104904455.027001298797180.901987016
#Sta/Elev= 29
9820.561 93.12459825.40492.740039835.43192.338669845.45891.385719865.51290.25426
9885.56688.997039895.58488.121659905.59186.983519925.60683.68415 9945.6280.59784
9965.63477.025759975.64176.188579985.647 74.98729995.72271.73817    999971.63272
10005.8671.2199510015.9773.0900110026.0774.1186810036.1875.5395110056.3977.64284
 10066.578.06117 10076.678.0672810086.8478.2682510107.4378.1219610117.7378.36722
10128.0278.9756110138.3279.9690310169.2185.4360610179.4786.88615
#Mann= 3 , 0 , 0
9820.561    0.04       09820.561    0.04       010179.47    0.04       0
#XS Ineff= 2 , 0
       0                               0
Bank Sta=9820.561,10179.47
Exp/Cntr=0.3,0.1

Type RM Length L Ch R = 1 ,16235.85,242.906900,242.906900,242.906900
XS GIS Cut Line= 2
904689.019942946796930.613234877904449.386529485797082.105622698
#Sta/Elev= 28
9872.987 83.38269889.57381.753189901.40480.990189913.23580.740719918.62480.45922
9925.06679.984179936.896 78.19939948.72776.001299956.05275.052759960.55874.55858
9974.76673.774539984.21972.68749 9993.4870.76291 9996.0570.3838510007.8870.34998
10012.1971.5597510019.71 72.718610031.5473.0926810043.3773.23732 10055.273.22531
10067.0373.5067510078.8674.1295210102.5375.0387910114.3675.8286110126.1977.01482
10138.0279.3012410143.1980.2255210156.4981.89198
#Mann= 3 , 0 , 0
9872.987    0.04       09872.987    0.04       010156.49    0.04       0
#XS Ineff= 2 , 0
       0                               0
Bank Sta=9872.987,10156.49
Exp/Cntr=0.3,0.1

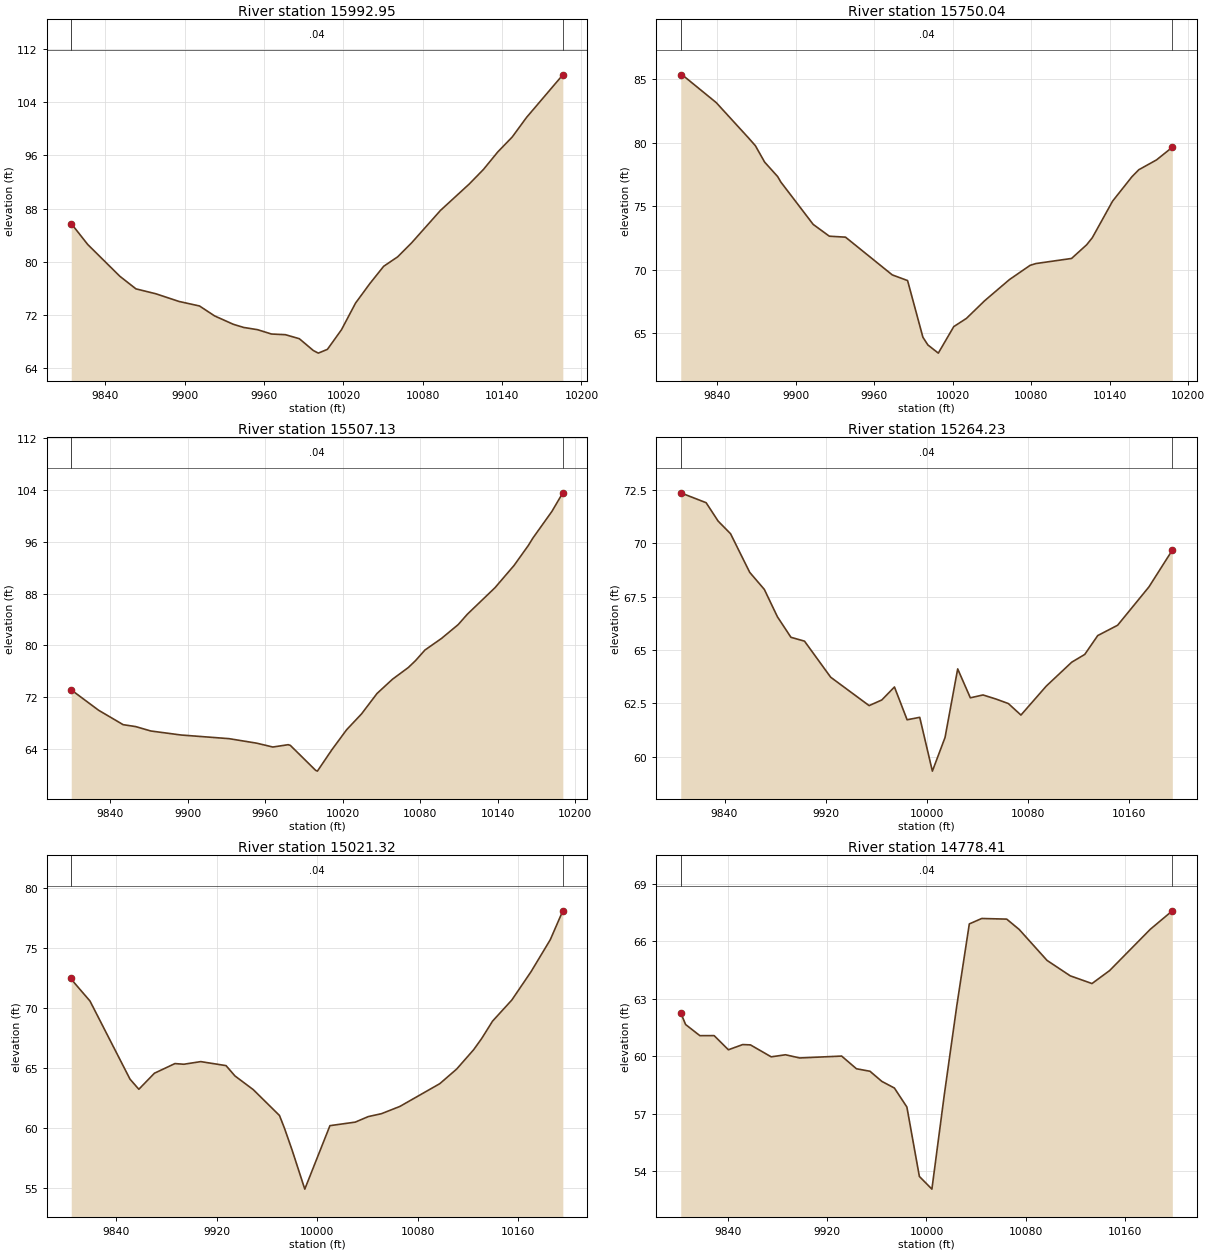
Type RM Length L Ch R = 1 ,15992.95,242.906800,242.906800,242.906800
XS GIS Cut Line= 6
 904715.35064486  796881.1593404904641.678711914796830.628931743
904615.231669175796815.925687912904560.886755765796798.082432089
904482.926021826796769.870288348904379.698369564796726.377137331
#Sta/Elev= 30
9814.18885.74242 9826.7482.578859850.99277.805029863.11875.917559878.116 75.1803
9895.79674.016529911.16573.342299922.60771.845139936.75170.582919944.552  70.112
9955.07869.771939965.60369.121419976.12869.019719986.65368.416379997.27466.63388
   1000166.2449710007.9166.8150610018.5469.7694410029.1773.77614 10039.8 76.6632
10050.4379.3135510061.0680.7434110071.6982.8699610093.3487.7143310115.05 91.6809
 10125.993.8926210136.7596.53257 10147.698.7640710158.45101.714310185.91108.1324
#Mann= 3 , 0 , 0
9814.188    0.04       09814.188    0.04       010185.91    0.04       0
#XS Ineff= 2 , 0
       0                               0
Bank Sta=9814.188,10185.91
Exp/Cntr=0.3,0.1

Type RM Length L Ch R = 1 ,15750.04,242.906900,242.906900,242.906900
XS GIS Cut Line= 6
904896.919315143796828.502507669904786.525550509796748.370143133
904718.353396184796706.316088347904703.419751224796691.082546726
904647.953280678796622.941690411904614.102494068796586.131744867
#Sta/Elev= 30
9812.10685.345099814.47785.238299839.19183.163429863.90480.382419869.13879.77197
9876.26178.475089886.16177.344289888.61876.911729913.33273.579429925.68872.65181
9938.04572.575919973.75469.609489985.47869.161699997.20264.70042   1000164.09709
10008.9663.4547710020.7765.5398410030.4666.1868510044.4667.5840510063.2969.23727
10079.1370.3596410083.5870.5009410110.8170.9011910122.2671.9681810126.6572.52943
10142.1875.4125510156.9577.3296510162.1977.8787810175.7778.6547810187.8279.65015
#Mann= 3 , 0 , 0
9812.106    0.04       09812.106    0.04       010187.82    0.04       0
#XS Ineff= 2 , 0
       0                               0
Bank Sta=9812.106,10187.82
Exp/Cntr=0.3,0.1

Type RM Length L Ch R = 1 ,15507.13,242.906900,242.906900,242.906900
XS GIS Cut Line= 6
904956.129300902796657.482320977904902.237509401796570.137528415
904881.461923762796544.676309835 904860.61030652796528.789418407
904777.860517173796480.847111758904685.443028554796399.180893086
#Sta/Elev= 30
9809.62473.137169830.81969.996249849.86367.768249859.54267.473929871.29266.79351
9894.793 66.17219931.794 65.61279953.24264.915639965.81464.318999977.69364.67906
9979.37564.57165    999960.7123510000.34  60.59810011.6263.9184810022.91 66.9719
10034.5569.4382710046.5372.5850910058.5274.7874910070.7776.5899910076.3577.65623
10083.6579.2915910096.5481.0900710109.4383.2220710116.4884.81414   1013888.93074
10152.65 92.338910163.7295.42488 10167.396.5804910181.96100.675710190.48103.5609
#Mann= 3 , 0 , 0
9809.624    0.04       09809.624    0.04       010190.48    0.04       0
#XS Ineff= 2 , 0
       0                               0
Bank Sta=9809.624,10190.48
Exp/Cntr=0.3,0.1

Type RM Length L Ch R = 1 ,15264.23,242.906800,242.906800,242.906800
XS GIS Cut Line= 6
905060.481697727796682.144313539905027.846721862796624.592202591
905010.037176196796572.105108181    905003.29062796494.466876518
905005.546111951796390.280857295904977.557901776796310.274535818
#Sta/Elev= 30
9805.34872.366749825.46271.903169834.95371.04147  9844.870.448369859.92368.64285
9871.567  67.8379881.86466.559959892.59865.59526 9903.3365.414919924.06763.72405
9954.49562.393879964.54462.657159974.55263.26731 9984.5661.729519994.56961.84436
10004.5859.32262 10014.660.8982910024.6264.1133310034.6462.7591810044.6662.89268
10054.6862.70662 10064.762.4913310074.7161.9505310094.74 63.307610114.9264.42913
10125.2164.79172 10135.565.6760910151.2566.1608110176.0867.9605810194.5669.68113
#Mann= 3 , 0 , 0
9805.348    0.04       09805.348    0.04       010194.56    0.04       0
#XS Ineff= 2 , 0
       0                               0
Bank Sta=9805.348,10194.56
Exp/Cntr=0.3,0.1

Type RM Length L Ch R = 1 ,15021.32,242.906900,242.906900,242.906900
XS GIS Cut Line= 6
905306.725035553796424.786788892905253.587469029796382.505258178
905198.596285949796353.159910464 905066.20554645796322.355285486
905023.939439333796288.776791713904978.471886164796236.024261748
#Sta/Elev= 30
9804.28172.474259806.56772.100399819.19670.561359851.08764.039689858.10763.19864
9870.49864.535119886.84465.34126 9893.9265.285639907.40365.505249927.53265.17091
9934.64264.309679949.19763.16792 9970.0761.013329973.87760.001339980.21458.09922
9990.23854.8654810010.2760.1615410030.4360.4560910040.7760.9172810051.2561.15859
10065.8861.7613710097.7563.6655310111.1964.8863110124.6366.4911310131.0467.42488
10139.7568.8841910155.0770.6422310170.3873.00723 10185.7 75.6746 10195.778.08713
#Mann= 3 , 0 , 0
9804.281    0.04       09804.281    0.04       0 10195.7    0.04       0
#XS Ineff= 2 , 0
       0                               0
Bank Sta=9804.281,10195.7
Exp/Cntr=0.3,0.1

Type RM Length L Ch R = 1 ,14778.41,242.906900,242.906900,242.906900
XS GIS Cut Line= 6
905332.606169679796348.409321702905260.322024188796214.380026013
905256.873839167796193.045003093905258.984579029796092.206059179
905245.188758404796038.765879756905219.453802344795978.876687916
#Sta/Elev= 30
9802.18362.25982  9806.161.649719817.58661.068939829.07361.070919840.55960.33215
9852.04660.603659858.29160.586919875.01959.963529886.50560.071159897.99259.90448
9931.71860.003239943.626 59.3411 9954.5459.210129964.04258.683289974.17258.33629
9984.24457.343189994.302 53.720310004.3853.0583110014.4358.0162610024.4762.65003
 10034.5 66.901410044.5167.1848410064.5967.1517110074.6666.6117210097.0864.99643
10115.7864.1907810133.2563.7889810147.4564.4659210180.1766.6190910197.9467.58455
#Mann= 3 , 0 , 0
9802.183    0.04       09802.183    0.04       010197.94    0.04       0
#XS Ineff= 2 , 0
       0                               0
Bank Sta=9802.183,10197.94
Exp/Cntr=0.3,0.1

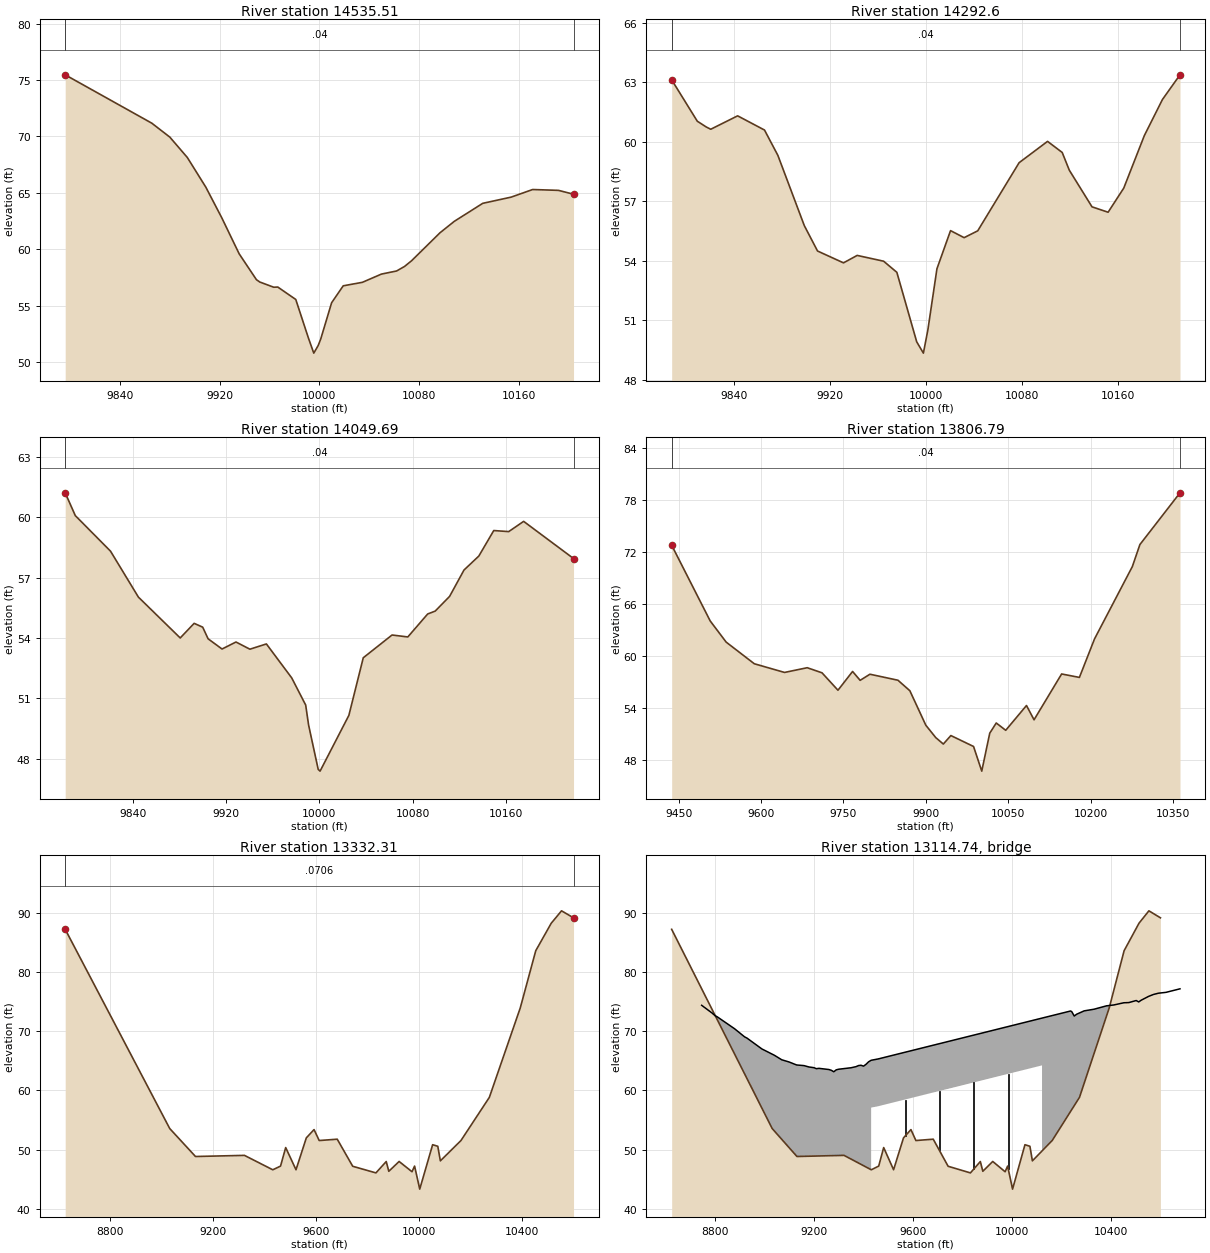
Type RM Length L Ch R = 1 ,14535.51,242.906900,242.906900,242.906900
XS GIS Cut Line= 6
905635.640782106 796333.13024007905489.297272531796192.559350332
905487.838790183796191.190836817905464.093630094796167.617131253
905442.460278598796136.064486631905379.165665451796021.216352787
#Sta/Elev= 30
 9796.0875.459659865.558 71.17569879.99369.94387 9894.0368.140739908.864 65.5143
9921.76262.778549935.62959.605869949.495 57.31329952.17157.108519963.36156.64736
9966.60656.663279981.04155.562369991.09352.177979995.47750.81035    999951.48174
   1000152.0389410009.7955.2707610019.0956.7719310034.4657.0810410049.7657.81103
10061.8858.0849810068.2358.4812710073.93 58.992510096.7761.4735310108.1962.48186
10131.0264.0773410153.8664.6287810171.0565.3002110191.7665.2267310203.8564.88474
#Mann= 3 , 0 , 0
 9796.08    0.04       0 9796.08    0.04       010203.85    0.04       0
#XS Ineff= 2 , 0
       0                               0
Bank Sta=9796.08,10203.85
Exp/Cntr=0.3,0.1

Type RM Length L Ch R = 1 , 14292.6,242.906800,242.906800,242.906800
XS GIS Cut Line= 6
905764.087517269796058.070239704905688.027985667 796019.50479635
905579.970065896795969.216194644905514.743288852795934.520368576
905453.194294731795892.398101375 905399.82777629795845.322753985
#Sta/Elev= 30
9787.90963.12022 9809.31 61.03279816.81160.741379820.52260.628939842.94661.30439
 9865.3760.589059876.52759.312099898.58755.771219909.61654.492939931.26553.89514
9942.70654.270659964.76653.978559975.79653.418439992.37449.915319997.93749.34629
10001.6950.5205110009.2553.5974510020.5955.5196610031.9355.1650410043.2855.50954
10077.8258.9438410101.54 60.017910113.7659.4592110119.6958.5649610138.6456.71867
10152.0756.4467510165.1457.66427 10182.360.3102110197.4262.1287510212.0563.37149
#Mann= 3 , 0 , 0
9787.909    0.04       09787.909    0.04       010212.05    0.04       0
#XS Ineff= 2 , 0
       0                               0
Bank Sta=9787.909,10212.05
Exp/Cntr=0.3,0.1

Type RM Length L Ch R = 1 ,14049.69,242.906900,242.906900,242.906900
XS GIS Cut Line= 6
905897.527917903795889.755265114905725.806001405795777.040516443
905716.294520183795770.160562838905714.684318242795768.974287276
905613.058560097795695.290207395905541.610365763795637.947257225
#Sta/Elev= 30
9781.85261.216929790.51860.085229820.76158.317079844.68456.034949880.56954.00546
9892.53154.731879899.86154.541149904.49353.964299916.45553.456179928.41653.80461
9940.37853.447369954.53253.708389976.26352.021229988.25650.671769990.74349.68199
    999947.4746110000.6147.3890710025.3150.1589710037.6753.0215310062.3754.15224
10075.9154.0557910092.95 55.196710099.4355.3414610111.7856.0716610124.1357.38039
10136.8658.0753110149.6859.3427810162.5159.2897210175.3359.7987410218.1457.95287
#Mann= 3 , 0 , 0
9781.852    0.04       09781.852    0.04       010218.14    0.04       0
#XS Ineff= 2 , 0
       0                               0
Bank Sta=9781.852,10218.14
Exp/Cntr=0.3,0.1

Type RM Length L Ch R = 1 ,13806.79,474.478200,474.478200,474.478200
XS GIS Cut Line= 2
906254.274849933795953.192993614 905581.97088092795316.813664166
#Sta/Elev= 30
9437.11172.777929507.21664.04342 9536.3161.596639587.57659.097569642.65458.09437
9683.96358.639599710.87158.052729739.96556.04224 9766.5858.207269780.34957.18206
9798.15257.888869849.196  57.1959870.88655.983029899.97952.000639918.04450.57459
9931.81349.831449945.58350.811279986.89149.5506110001.8146.7058710016.3551.08062
 10028.252.2605510045.4551.4169410083.2854.2780810097.0552.6293510147.2757.91816
10179.6657.51979 10207.261.9658710276.0570.3090710289.8272.8521510362.84  78.822
#Mann= 3 , 0 , 0
9437.111    0.04       09437.111    0.04       010362.84    0.04       0
#XS Ineff= 2 , 0
       0                               0
Bank Sta=9437.111,10362.84
Exp/Cntr=0.3,0.1

Type RM Length L Ch R = 1 ,13332.31,438.226700,438.226700,438.226700
XS GIS Cut Line= 3
907610.659343361 795304.70753018906829.409343361795318.596419069
905638.437121139795276.929752402
#Sta/Elev= 30
8625.31687.253039031.039 53.55479131.05548.826139321.08549.016459431.11446.57755
9461.13247.205899481.14450.338399521.16946.585479561.19351.975779591.21153.37781
9611.22451.527219681.266 51.75429741.30347.173569831.35846.052569871.38347.97307
9881.38946.324869921.41347.987449971.44446.24805 9981.4547.2065110001.4643.30787
10051.4950.8210110071.5150.5552410081.5148.0884810161.5651.5349810271.6358.82914
 10391.773.9657810451.7483.6331410511.7788.27623 10551.890.3815110598.3989.20001
#Mann= 3 , 0 , 0
8625.316  0.0706       08625.316  0.0706       010598.39  0.0706       0
#XS Ineff= 2 , 0
       09391.571                       0
Bank Sta=8625.316,10598.39
Exp/Cntr=0.3,0.1

Type RM Length L Ch R = 3 ,13114.74,,,
BEGIN DESCRIPTION:
END DESCRIPTION:
Bridge Culvert--1,0,-1,-1, 0
Deck Dist Width WeirC Skew NumUp NumDn MinLoCord MaxHiCord MaxSubmerge Is_Ogee
162.613350,113.000000,2.6,0, 52, 53, , , 0.95, 0, 0,0,,
 8746.39 8789.43 8799.44 8809.44 8879.48 8919.50 8929.51 8989.54 9039.57 9069.59
 9099.60 9129.62 9159.64 9179.65 9199.66 9209.66 9219.67 9259.69 9269.70 9279.70
 9289.71 9299.71 9349.74 9369.75 9379.76 9389.77 9399.77 9409.78 9419.78 9430.49
 9430.49 9458.9710120.4910120.4910235.6810240.3710250.3810260.3910290.4110330.44
10380.4810410.5010450.5310470.5410500.5610510.5710520.5810550.6010570.6110590.63
10620.6510677.36
   74.40   73.06   72.68   72.45   70.43   69.07   68.85   67.02   65.96   65.19
   64.81   64.31   64.20   63.97   63.85   63.68   63.74   63.54   63.41   63.16
   63.49   63.59   63.84   64.03   64.21   64.26   64.11   64.42   64.83   65.10
   65.10   65.33   72.24   72.24   73.44   73.33   72.59   72.90   73.46   73.74
   74.31   74.46   74.83   74.86   75.21   74.97   75.26   75.91   76.24   76.45
   76.59   77.19
 -925.60 -926.94 -927.32 -927.55 -929.57 -930.93 -931.15 -932.98 -934.04 -934.81
 -935.19 -935.69 -935.80 -936.03 -936.15 -936.32 -936.26 -936.46 -936.59 -936.84
 -936.51 -936.41 -936.16 -935.97 -935.79 -935.74 -935.89 -935.58 -935.17 -934.90
   57.10   57.33   64.24 -927.76 -926.56 -926.67 -927.41 -927.10 -926.54 -926.26
 -925.69 -925.54 -925.17 -925.14 -924.79 -925.03 -924.74 -924.09 -923.76 -923.55
 -923.41 -922.81
 8746.39 8789.43 8799.44 8809.44 8879.48 8919.50 8929.51 8989.54 9039.57 9069.59
 9099.60 9129.62 9159.64 9179.65 9199.66 9209.66 9219.67 9259.69 9269.70 9279.70
 9289.71 9299.71 9349.74 9369.75 9379.76 9389.77 9399.77 9409.78 9419.78 9429.79
 9458.97 9554.11 9554.1110235.6810240.3710244.1110244.1110250.3810260.3910290.41
10330.4410380.4810410.5010450.5310470.5410500.5610510.5710520.5810550.6010570.61
10590.6310620.6510677.36
   74.40   73.06   72.68   72.45   70.43   69.07   68.85   67.02   65.96   65.19
   64.81   64.31   64.20   63.97   63.85   63.68   63.74   63.54   63.41   63.16
   63.49   63.59   63.84   64.03   64.21   64.26   64.11   64.42   64.83   65.09
   65.33   66.33   66.33   73.44   73.33   73.05   73.05   72.59   72.90   73.46
   73.74   74.31   74.46   74.83   74.86   75.21   74.97   75.26   75.91   76.24
   76.45   76.59   77.19
 -925.60 -926.94 -927.32 -927.55 -929.57 -930.93 -931.15 -932.98 -934.04 -934.81
 -935.19 -935.69 -935.80 -936.03 -936.15 -936.32 -936.26 -936.46 -936.59 -936.84
 -936.51 -936.41 -936.16 -935.97 -935.79 -935.74 -935.89 -935.58 -935.17 -934.91
 -934.67 -933.67   58.33   65.44   65.33   65.05 -926.95 -927.41 -927.10 -926.54
 -926.26 -925.69 -925.54 -925.17 -925.14 -924.79 -925.03 -924.74 -924.09 -923.76
 -923.55 -923.41 -922.81
Pier Skew, UpSta & Num, DnSta & Num=  ,9567.29, 2 ,9690.91, 2 , 0 , 0 , 0 ,,
    4.00    4.00
 -933.54   66.46
    4.00    4.00
 -932.25   67.75
Pier Skew, UpSta & Num, DnSta & Num=  ,9706.09, 2 ,9829.71, 2 , 0 , 0 , 0 ,,
    4.00    4.00
 -932.09   67.91
    4.00    4.00
 -930.80   69.20
Pier Skew, UpSta & Num, DnSta & Num=  ,9844.89, 2 ,9968.51, 2 , 0 , 0 , 0 ,,
    4.00    4.00
 -930.64   69.36
    4.00    4.00
 -929.35   70.65
Pier Skew, UpSta & Num, DnSta & Num=  ,9983.69, 2 ,10107.31, 2 , 0 , 0 , 0 ,,
    4.00    4.00
 -929.19   70.81
    4.00    4.00
 -927.90   72.10
BR Coef=-1 , 0 , 0 ,, 0 ,,,0.8,0,1,0,
WSPro=,,,, 1 ,,,, 0 ,,,, 0 ,,,,-1 ,-1 ,-1 , 0 , 0 , 0 , 0 , 0
BC Design=,, 0 ,, 0 ,,,,,,