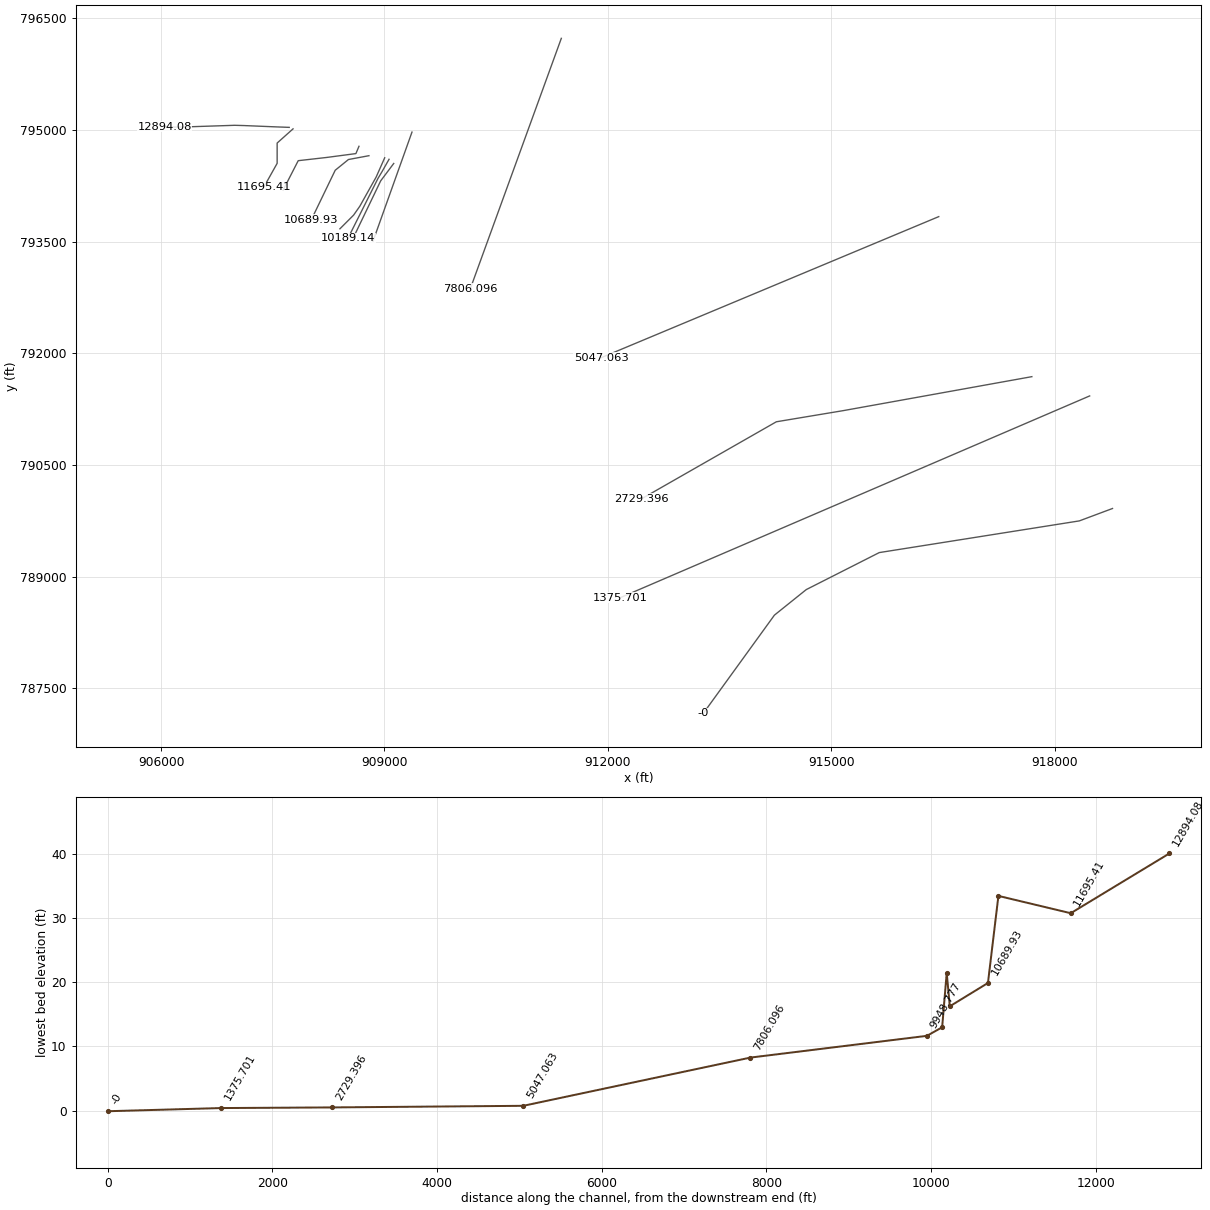
HEC-RAS study 12017_ras.prj: 12017

--- 12017_ras.g01 (geometry) --- (continued)

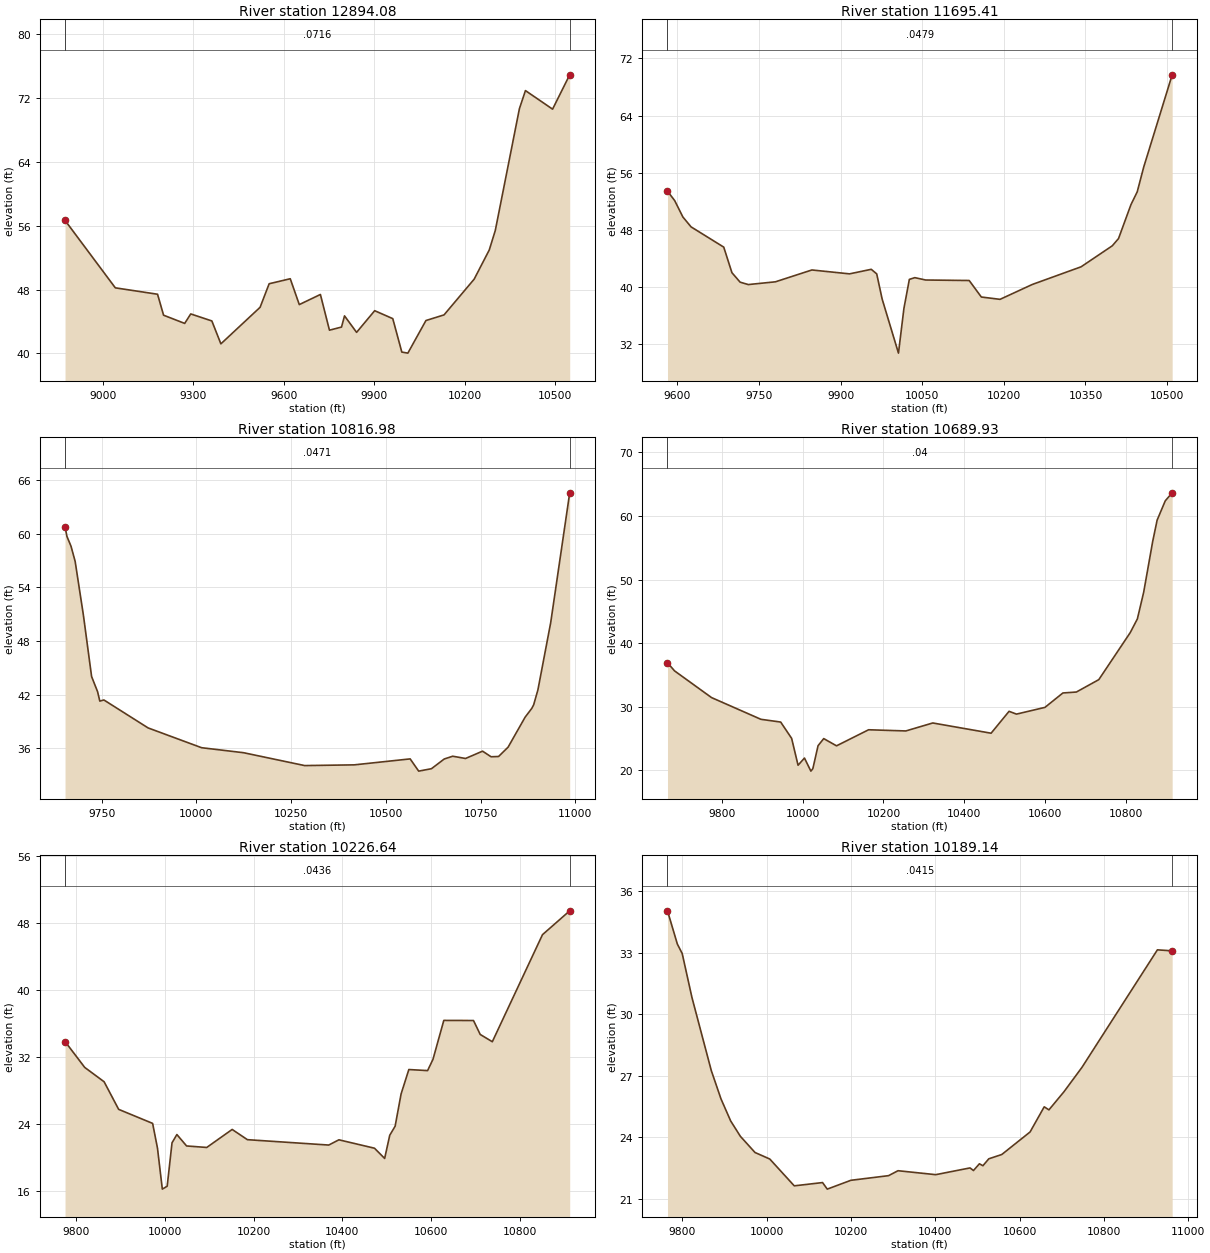
Type RM Length L Ch R = 1 ,12894.08,1198.666300,1198.666300,1198.666300
XS GIS Cut Line= 6
907721.770454472795033.874196846907534.270454472795040.818641291
907114.131565583795058.179752402906989.131565583795061.651974624
 906249.54823225795037.346419069906048.159343361795040.818641291
#Sta/Elev= 30
8874.44256.655039041.32748.212139181.443  47.412 9201.4644.78672 9271.52 43.7596
9291.53744.946289361.59644.070029391.62241.201649521.71545.776989551.72648.72386
9621.75549.350869651.77246.115849721.80947.382429751.82642.912429791.84743.30316
9801.85344.702129841.874 42.63929901.90745.351829961.93944.357979991.955 40.1714
10011.9740.04079   1007244.1222810132.0344.8253510232.0849.3022710282.1152.95414
10302.1255.3935110382.1570.6374510402.1672.9002910492.17 70.577210549.02 74.8733
#Mann= 3 , 0 , 0
8874.442  0.0716       08874.442  0.0716       010549.02  0.0716       0
#XS Ineff= 2 , 0
       09559.484                       0
Bank Sta=8874.442,10549.02
Exp/Cntr=0.3,0.1

Type RM Length L Ch R = 1 ,11695.41,878.436300,878.436300,878.436300
XS GIS Cut Line= 4
907773.104932124 795013.81496152907559.519792562794823.389656369
907559.519792562794550.618273314907379.387747149794228.953906503
#Sta/Elev= 30
9581.74653.414349594.99252.086439610.01949.796429625.04548.412669685.15245.57523
9700.17941.998539715.20640.672119730.233 40.33399780.16740.720289847.15442.37748
9916.28341.833019956.283 42.46919966.28341.829929976.283 38.304510006.28 30.7354
10016.2836.9856510026.2841.0589710036.2841.3022410056.2840.9719710136.2840.90211
10158.5738.5903910192.9538.2652710252.2540.3479110341.9542.8214710399.2545.76084
10410.71 46.774110433.6451.53543 10445.153.3177310456.9156.7531410509.3369.69789
#Mann= 3 , 0 , 0
9581.746  0.0479       09581.746  0.0479       010509.33  0.0479       0
#XS Ineff= 2 , 0
       09874.752        10054.97       0
Bank Sta=9581.746,10509.33
Exp/Cntr=0.3,0.1

Type RM Length L Ch R = 1 ,10816.98,127.050700,127.050700,127.050700
XS GIS Cut Line= 5
908658.325269586794779.643302483908617.152230634794681.857334972
908228.581675528794630.391036283907842.584435355794586.644682396
907639.292555531794190.354182486
#Sta/Elev= 30
9653.44860.800599658.486 59.70159669.33758.593199680.18756.901349701.88850.90141
9723.588  44.0159739.32642.323289745.28941.265529756.13941.389859872.68138.26418
 10013.936.0489610124.8635.4879510285.9534.0492710416.7834.1298310564.3134.79677
10586.7933.42851 10620.5  33.69910654.2234.78654 10676.735.0969810710.4134.84364
10755.3735.6629210777.85 35.0359 10797.635.0643110822.8136.1140810867.7639.47056
10885.2340.4472310890.2440.8510910901.4842.53001 10935.2  50.04610985.3764.57605
#Mann= 3 , 0 , 0
9653.448  0.0471       09653.448  0.0471       010985.37  0.0471       0
#XS Ineff= 2 , 0
       0                10148.77       0
Bank Sta=9653.448,10985.37
Exp/Cntr=0.3,0.1

Type RM Length L Ch R = 1 ,10689.93,463.292400,463.292400,463.292400
XS GIS Cut Line= 4
908792.137646179794653.550870693 908516.79294819794602.084572003
 908339.23421771794457.978935672  908017.5698509793791.490367641
#Sta/Elev= 30
9665.59136.929359683.02535.648069774.58431.445449896.66228.031199945.70427.59528
9972.81525.025759988.68420.8053610004.5521.9329410020.4219.8787410025.2920.26702
10038.1723.8744810052.1624.99444 10083.923.8584310163.2426.3838910255.4226.19801
10322.0427.4516510466.3925.84222 10510.829.2836110529.2328.8461510599.6329.90521
10644.0532.1707310677.3632.3182210732.8834.26887 10810.641.6580910828.3243.82049
10843.9148.0134210866.1255.9700210877.2259.3577510897.3462.3903710914.4363.64913
#Mann= 3 , 0 , 0
9665.591    0.04       09665.591    0.04       010914.43    0.04       0
#XS Ineff= 2 , 0
       0                10169.01       0
Bank Sta=9665.591,10914.43
Exp/Cntr=0.3,0.1

Type RM Length L Ch R = 1 ,10226.64,37.496200,37.496200,37.496200
XS GIS Cut Line= 5
909003.865636892794625.560678871908889.392214994794367.434335376
908669.423678798793974.633377882908586.374333499793855.670802184
908402.319027702793671.615496387
#Sta/Elev= 30
9774.91233.879759819.28330.78884 9863.0429.072429895.85825.776119972.43224.09977
9983.37221.147499994.31116.2475210005.2516.5962710016.1921.7835610027.1322.76716
10049.0121.4033710094.46 21.225210151.7623.3774810186.1522.1546110369.5321.51218
10392.45 22.139310472.6821.13476 10495.619.9133910507.0622.6776310519.2323.76379
10532.6827.6207410550.1530.5324610592.41 30.4058 10604.631.7571210628.9936.40207
10695.9436.3867510711.0834.7230310738.3733.85335 10851.546.6439110912.8649.49096
#Mann= 3 , 0 , 0
9774.912  0.0436       09774.912  0.0436       010912.86  0.0436       0
#XS Ineff= 2 , 0
       0                10448.49       0
Bank Sta=9774.912,10912.86
Exp/Cntr=0.3,0.1

Type RM Length L Ch R = 1 ,10189.14,55.294200,55.294200,55.294200
XS GIS Cut Line= 4
909062.224636291794605.359486772908967.952406493794439.260796174
908914.082560894794349.477720176  908510.0587189793543.674613089
#Sta/Elev= 30
9764.90435.041979788.31433.420569799.81332.95831 9822.8130.822829868.803 27.2472
  9891.825.864899914.79724.787739937.794 24.03829972.52223.2486510007.5122.93084
 10065.621.6214610132.7221.7812610143.9121.4612910199.8421.8914910289.3422.11872
10311.7122.35943 10401.222.1671610482.46  22.49610490.69 22.368710504.7722.69774
10513.0722.6028710527.0822.9413910557.8123.1503810624.93 24.249810658.4925.47723
10669.6825.3291810705.5726.2190910747.99 27.402510926.97 33.137510962.0133.08966
#Mann= 3 , 0 , 0
9764.904  0.0415       09764.904  0.0415       010962.01  0.0415       0
#XS Ineff= 2 , 0
       0                10472.11       0
Bank Sta=9764.904,10962.01
Exp/Cntr=0.3,0.1

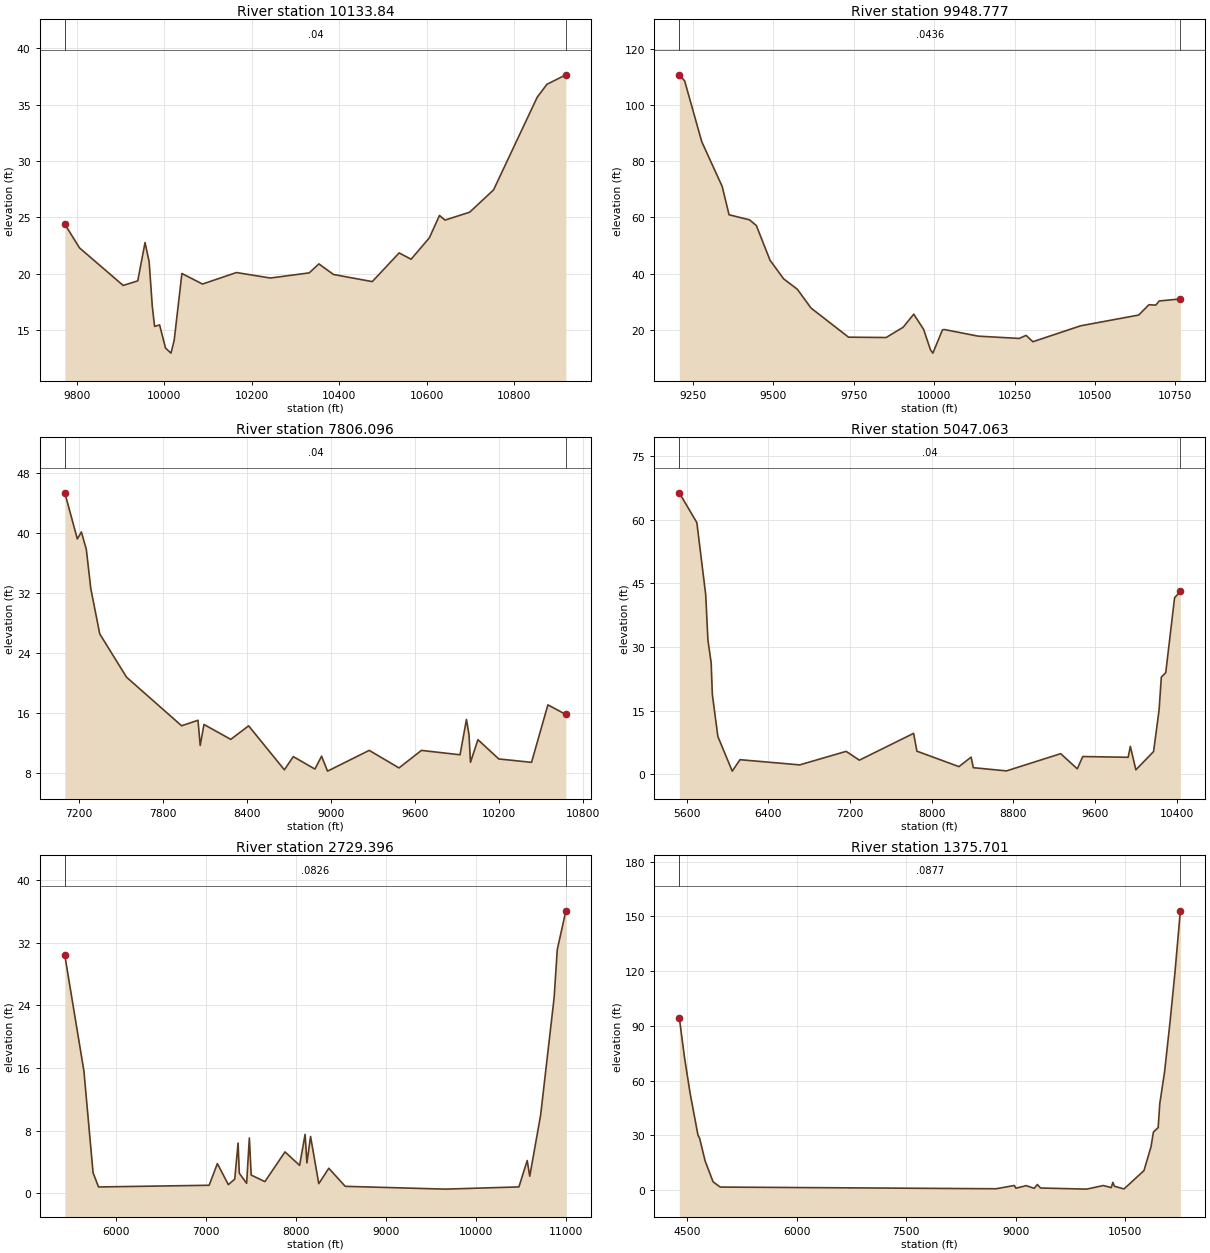
Type RM Length L Ch R = 1 ,10133.84,185.067500,185.067500,185.067500
XS GIS Cut Line= 3
 909125.07278949794549.245064273908949.995791293794315.809066676
908579.640602799793545.919189989
#Sta/Elev= 30
9772.57524.41049 9806.0322.31097 9906.0318.979499939.36319.38722 9956.0322.77724
9965.38121.089669972.69617.105339977.881  15.3529989.36315.4845710002.8813.43338
10015.3812.98495 10022.714.1235910040.3820.0379310087.4619.1049210165.1420.12349
10242.8219.6377810331.5920.0944810353.7920.8887810387.0819.9528410475.8519.32041
10537.2621.8617810564.6321.3019610606.4623.2017510629.5325.1775610642.3124.77001
10698.7325.4714210753.2727.4456210853.1535.6542510875.3436.7976210918.7137.63741
#Mann= 3 , 0 , 0
9772.575    0.04       09772.575    0.04       010918.71    0.04       0
#XS Ineff= 2 , 0
       0                10490.95       0
Bank Sta=9772.575,10918.71
Exp/Cntr=0.3,0.1

Type RM Length L Ch R = 1 ,9948.777,2142.680900,2142.680900,2142.680900
XS GIS Cut Line= 2
909370.266381288794970.706461803908846.084417698793502.996963751
#Sta/Elev= 30
9207.295110.80359223.973108.61599277.06686.974759340.77870.987669362.015 60.9452
9425.72759.144299446.96457.101789489.43944.752519531.91338.106149574.38834.40742
9616.862 27.72399733.66717.334629850.47217.211879903.56520.875499936.52425.53384
9967.27720.100339988.51412.844889995.98911.6531910025.7219.9247310030.9920.07231
10137.1717.70044 10264.616.8859510285.8417.9733410307.0715.7199910455.7321.39145
10636.2525.2257210668.1128.8982510689.3428.7510310699.9630.23564 10765.830.96016
#Mann= 3 , 0 , 0
9207.295  0.0436       09207.295  0.0436       0 10765.8  0.0436       0
#XS Ineff= 2 , 0
       0                10761.49       0
Bank Sta=9207.295,10765.8
Exp/Cntr=0.3,0.1

Type RM Length L Ch R = 1 ,7806.096,2759.033500,2759.033500,2759.033500
XS GIS Cut Line= 2
911375.474714622796229.387017359910152.272759443792864.269192167
#Sta/Elev= 30
7097.89945.325217187.10439.185427216.37540.111847251.529 37.78527283.44932.56706
 7347.2926.548467538.813  20.7787932.49814.30867 8049.54 15.04428065.25911.68657
8092.10114.481338283.62312.499818411.30514.298968666.6698.445229 8730.5110.20377
 8884.878.5472598932.67310.262088975.2338.2703429273.15711.03553 9485.968.695138
9645.93811.030859922.20710.448879967.92815.146539986.04813.133099996.6889.443809
10049.8912.4588910198.859.89337310432.939.43808810549.9817.0943110678.4315.81402
#Mann= 3 , 0 , 0
7097.899    0.04       07097.899    0.04       010678.43    0.04       0
#XS Ineff= 2 , 0
       0 9653.46        10062.78       0
Bank Sta=7097.899,10678.43
Exp/Cntr=0.3,0.1

Type RM Length L Ch R = 1 ,5047.063,2317.667200,2317.667200,2317.667200
XS GIS Cut Line= 2
916443.593354119793835.385610415911912.736791679791941.893315664
#Sta/Elev= 30
5526.95666.356245698.84159.331725785.546 42.33485807.22231.683485839.16526.25072
5850.57518.827865904.7658.9255196045.6610.7650666121.5283.4627516706.7872.235743
7161.9885.4249737291.4733.3485697823.1139.6660087855.6285.4673568267.4761.825999
8386.6964.0655368408.3721.5751328733.5160.8198279264.5844.8794919427.1561.313716
9481.3464.2075739925.7094.0258689947.3856.60114310001.581.07214610174.995.379698
10229.1815.2047610250.8522.9159110294.2123.9598310380.9141.6338110437.5543.10797
#Mann= 3 , 0 , 0
5526.956    0.04       05526.956    0.04       010437.55    0.04       0
#XS Ineff= 2 , 0
       07993.053        10427.49       0
Bank Sta=5526.956,10437.55
Exp/Cntr=0.3,0.1

Type RM Length L Ch R = 1 ,2729.396,1353.694600,1353.694600,1353.694600
XS GIS Cut Line= 4
917693.791141421791686.388017838915161.301658248 791230.26760017
914262.676357767791080.496716756 912451.81022195790045.716067718
#Sta/Elev= 30
5428.65730.395085640.80815.608855742.4172.6177685803.3820.7926027032.8511.009105
7124.299 3.78198 7246.231.0911877317.3561.7927587354.6236.4165297368.1612.551529
7449.4481.2563937479.9317.0536857500.2522.3149297652.6661.4767377876.2065.276085
8038.6973.5529758099.5247.517764  8119.83.8657878160.3527.2455838251.5931.213166
8363.1113.1830018545.5940.8735459658.8770.51556810476.620.80030510568.764.174828
10596.912.16038410717.859.98023810868.22 25.024910902.7731.1424210998.5836.10293
#Mann= 3 , 0 , 0
5428.657  0.0826       05428.657  0.0826       010998.58  0.0826       0
#XS Ineff= 2 , 0
       08291.082                       0
Bank Sta=5428.657,10998.58
Exp/Cntr=0.3,0.1

Type RM Length L Ch R = 1 ,1375.701,1375.701200,1375.701200,1375.701200
XS GIS Cut Line= 2
  918469.8766282791427.692855578912165.883989978 788718.20141928
#Sta/Elev= 30
4392.70394.402734463.31872.76471 4539.5153.217044648.35629.964914670.12528.37121
4746.31715.826924855.1624.4239744953.1231.546974 8730.060.6176338980.4042.415763
9002.1730.9329839143.6722.3230189252.5180.8509599296.0562.9504079339.5941.031646
9970.8970.414991 10198.8 2.3911810308.321.24636310330.094.12930110351.861.967434
10482.470.52073110755.9310.5805910852.5523.67343 10885.231.6928910950.5134.18168
10972.2847.2920411037.5864.5615311113.7792.4926211179.08118.791211254.31153.0968
#Mann= 3 , 0 , 0
4392.703  0.0877       04392.703  0.0877       011254.31  0.0877       0
#XS Ineff= 2 , 0
       07691.639                       0
Bank Sta=4392.703,11254.31
Exp/Cntr=0.3,0.1

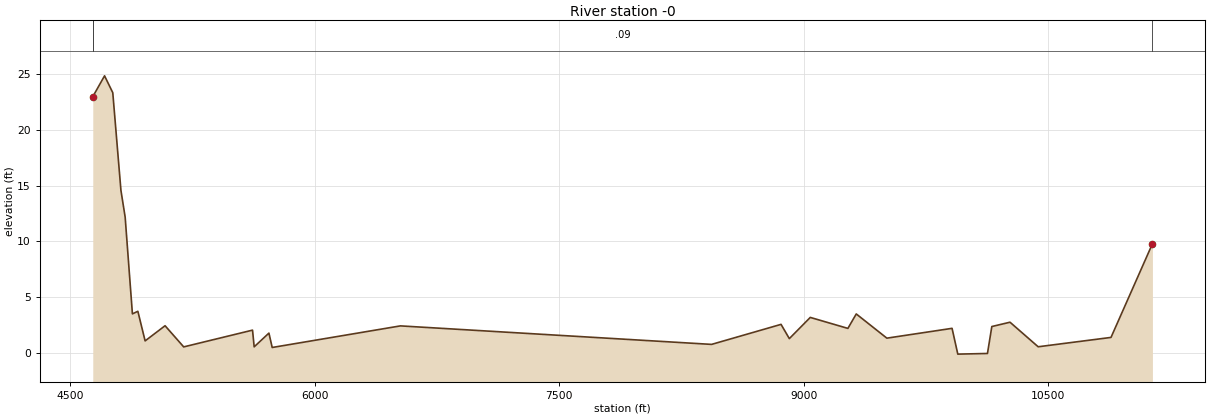
Type RM Length L Ch R = 1 ,      -0,0.000000,0.000000,0.000000
XS GIS Cut Line= 6
 918776.76281383789916.265286156918330.956965536789749.573892191
915644.653145641789324.092720374914664.334636003788827.125698134
 914236.96389398 788484.17386809913281.637279642787165.029976327
#Sta/Elev= 30
 4637.8122.942054710.12124.811264760.50323.303844810.603 14.56264836.48712.17492
4881.0023.5196954914.3893.7527894958.9041.1028425081.3212.4605315195.575 0.56783
5617.8472.0666955627.9010.5741045718.3881.8003735738.4970.5149286525.1072.446514
8433.8980.7916248859.9372.5823258910.8451.3080329039.2753.2045299270.0652.221963
9321.3523.5136439509.128 1.349479909.0362.2272999944.322-0.0789110126.24-0.02057
   101532.38864510264.552.77538510437.250.57888210884.071.41504811138.219.789694
#Mann= 3 , 0 , 0
 4637.81    0.09       0 4637.81    0.09       011138.21    0.09       0
#XS Ineff= 2 , 0
       07653.933                       0
Bank Sta=4637.81,11138.21
Exp/Cntr=0.3,0.1